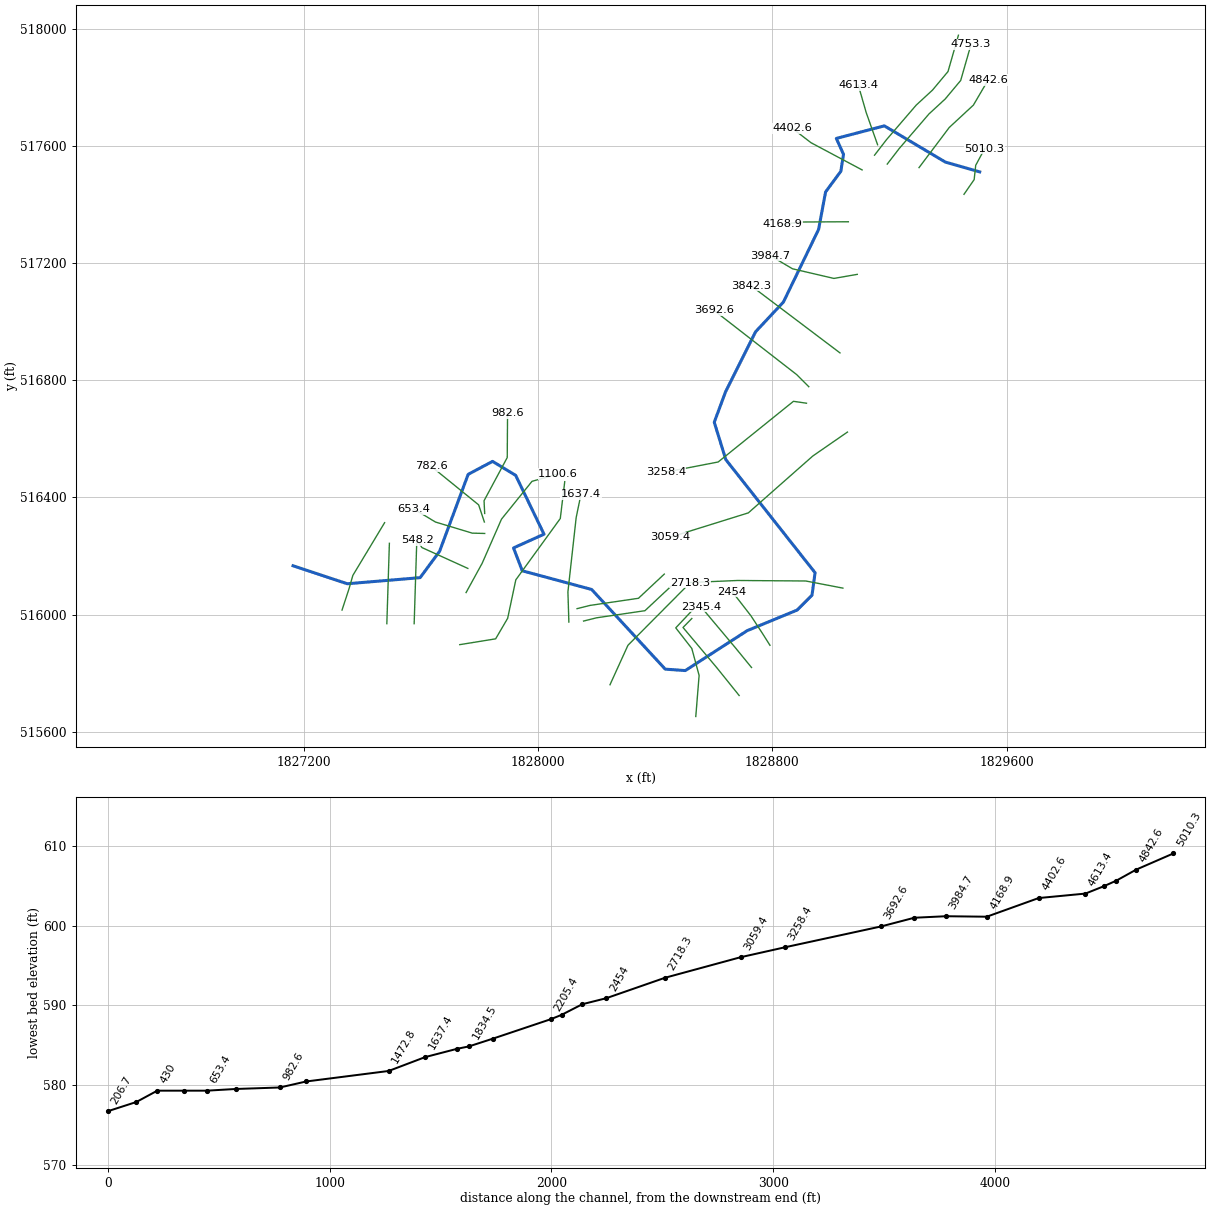
--- PINCHCR.prj (project) ---

Proj Title=PINCHCR
Current Plan=p01
Default Exp/Contr=0,0
English Units
Geom File=g01
Flow File=f01
Plan File=p01
BEGIN DESCRIPTION:
END DESCRIPTION:
DSS Export Rating Curves= 0
DSS Export Rating Curve Sorted= 0
DSS Export Volume Flow Curves= 0
DXF OffsetX= 0
DXF OffsetY= 0
DXF ScaleX= 0
DXF ScaleY= 0

--- PINCHCR.p01 (plan) ---

Plan Title=Floodplain
Program Version=4.00
Geom File=g01
Flow File=f01
K Sum by GR=0
Std Step Tol=0.01
Critical Tol=0.01
Num of Std Step Trials=20
Max Error Tol=0.3
Flow Tol Ratio=0.001
Split Flow NTrial=30
Split Flow Tol=0.02
Split Flow Ratio=0.02
Log Output Level=0
Friction Slope Method=1
Unsteady Friction Slope Method=2
Unsteady Bridges Friction Slope Method=1
Global Log Level=0
CheckData=False
Run HTab=0
Run UNet=0
Run PostProcess=0
UNET Theta=0
UNET Theta Warmup=0
UNET ZTol=0
UNET ZSATol=0
UNET MxIter=0
UNET MaxInSteps=0
UNET DtIC=0
UNET DtMin=0
UNET MaxCRTS=0
UNET WFStab=0
UNET SFStab=0
UNET WFX=0
UNET SFX=0
UNET DSS MLevel=0
UNET DZMax Abort=0
UNET Convert EG Bridges=0
UNET Use Existing IB Tables=0
UNET Froude Limit=0
UNET Froude Power=0
Write IC File=0
Echo Input=False
Echo Output=False
Write Detailed=0

--- PINCHCR.f01 (steady flow) ---

Flow Title=NFF Regression Equation
Program Version=4.10
Number of Profiles= 1
Profile Names=P100yr
River Rch & RM=PINCHCR,Main            ,5010.3
785.8929
River Rch & RM=PINCHCR,Main            ,4168.9
1064.768
River Rch & RM=PINCHCR,Main            ,1943.2
1214.643
River Rch & RM=PINCHCR,Main            ,548.2
1222.593
Boundary for River Rch & Prof#=PINCHCR,Main            , 1
Up Type= 0
Dn Type= 3
Dn Slope=0.01
DSS Import GetInterval= 0
DSS Import GetPeak= 0
DSS Import FillOption= 0

--- PINCHCR.g01 (geometry) ---

Geom Title=USGS 10m DEM
Program Version=4.10

River Reach=PINCHCR         ,Main
Reach XY= 30
     1829508.506      517511.807     1829391.094       517545.36
     1829182.761      517669.058     1829018.785      517626.158
     1829043.322       517571.73     1829034.106      517513.893
     1828982.022      517443.364     1828958.151      517315.326
     1828838.005      517067.297     1828742.953      516965.734
     1828640.088      516760.005     1828601.769      516656.757
     1828641.208      516529.122     1828946.078      516142.817
     1828935.661      516065.995      1828884.88      516015.213
     1828714.307      515944.901     1828502.948       515808.54
     1828434.359       515813.39     1828183.057      516085.526
     1827946.078      516149.328      1827916.13      516227.453
     1828020.296      516274.328     1827923.555      516475.236
     1827844.515      516523.026     1827761.182      516478.755
     1827663.526      516215.734     1827597.119       516125.89
     1827348.421      516105.057     1827163.125      516166.482

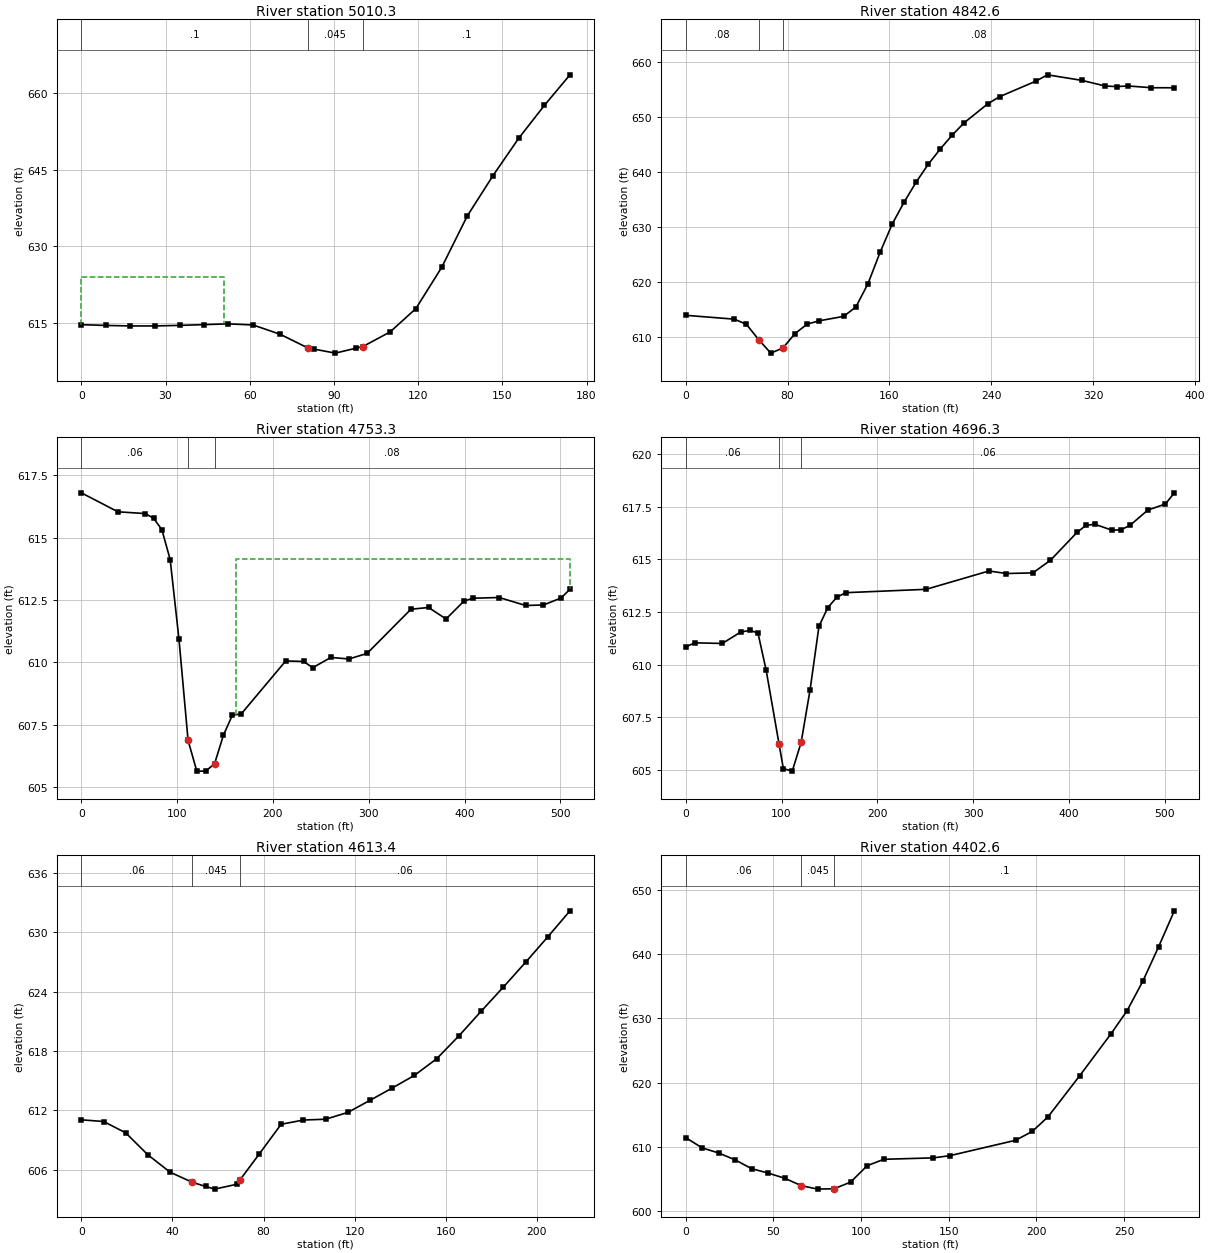
Type RM Length L Ch R = 1 ,5010.3  ,179.8,167.7,156.6
XS GIS Cut Line= 4
     1829454.833      517435.289     1829489.556      517485.636
     1829494.764      517534.248     1829525.146      517590.671
#Sta/Elev= 22
       0  614.64     8.7  614.49    17.5  614.39    26.2  614.39      35   614.5
    43.7  614.65    52.4   614.8    61.2  614.58    70.9  612.74    80.7  610.08
    82.9  609.85    90.5  609.06    97.9  610.03   100.3  610.35     110  613.21
   119.2  617.79   128.4  625.88   137.5  635.94   146.7  643.88   155.8  651.15
     165  657.64   174.1  663.62
#Mann= 3 , 0 , 0
       0      .1       0    80.7    .045       0   100.3      .1       0
#XS Ineff= 2 , 0
            50.7  623.93
Permanent Ineff=
       F       F
Bank Sta=80.7,100.3
XS Rating Curve= 0 ,0
Exp/Cntr=0.3,0.1

Type RM Length L Ch R = 1 ,4842.6  ,90.8,89.3,88
XS GIS Cut Line= 4
     1829301.188      517526.435     1829404.486      517663.588
     1829486.952      517739.977     1829537.299      517825.914
#Sta/Elev= 30
       0  613.92    38.2  613.22    47.7  612.27    57.2  609.51    66.8  607.03
    76.3  607.96    85.8  610.59    95.4  612.32   104.9  612.92     124  613.73
   133.6  615.43   143.1  619.67   152.6  625.38   162.2  630.57   171.7  634.63
   181.1  638.24   190.4  641.43   199.8   644.2   209.2  646.74   218.5  648.97
   237.3  652.48   246.6  653.77   274.7  656.56   284.1  657.74   311.3  656.72
   329.4   655.7   338.4   655.6   347.5  655.71   365.6  655.39   383.7  655.38
#Mann= 3 , 0 , 0
       0     .08       0    57.2    .045       0    76.3     .08       0
Bank Sta=57.2,76.3
XS Rating Curve= 0 ,0
Exp/Cntr=0.3,0.1

Type RM Length L Ch R = 1 ,4753.3  ,56.9,57,56.9
XS GIS Cut Line= 6
     1829192.681      517538.588     1829233.479      517591.539
     1829335.042      517709.595     1829390.597       517760.81
     1829443.549      517824.178     1829479.139       517948.31
#Sta/Elev= 30
       0  616.79    38.2  616.03    66.8  615.96    75.4  615.77      84  615.32
    92.7  614.12   101.9  610.93   111.4  606.88   120.5  605.65   129.8  605.65
   139.1  605.95   148.3  607.09   157.6  607.89   166.9  607.94   213.3  610.06
     232  610.04   241.5  609.79   260.4   610.2   279.3  610.14   298.2  610.36
     344  612.13   362.4   612.2   380.7  611.74   399.2  612.45   408.4  612.57
   436.1   612.6   463.8  612.28   482.3   612.3   500.7  612.58     510  612.93
#Mann= 3 , 0 , 0
       0     .06       0   111.4    .045       0   139.1     .08       0
#XS Ineff= 2 , 0
                          161.03          614.16
Permanent Ineff=
       F       F
Bank Sta=111.4,139.1
XS Rating Curve= 0 ,0
Exp/Cntr=0.3,0.1

Type RM Length L Ch R = 1 ,4696.3  ,58.5,82.9,106.6
XS GIS Cut Line= 6
     1829149.278       517568.97     1829190.077      517621.921
     1829291.639      517739.977     1829347.195      517791.192
     1829400.146       517854.56     1829435.736      517978.692
#Sta/Elev= 30
       0  610.84     9.6  611.03    38.2     611    57.3  611.54    66.8  611.62
    75.4   611.5      84  609.72    97.4  606.23   101.9  605.06   111.2  604.94
   120.5  606.31   129.8   608.8   139.1  611.82   148.3   612.7   157.6  613.19
   166.9  613.41   250.9  613.57   316.5  614.44   334.8  614.32   362.4  614.35
   380.7  614.95   408.4  616.27   417.6   616.6   426.9  616.66   445.3  616.37
   454.6   616.4   463.8  616.61   482.3  617.33   500.7  617.62     510  618.15
#Mann= 3 , 0 , 0
       0     .06       0    97.4    .045       0   120.5     .06       0
Bank Sta=97.4,120.5
XS Rating Curve= 0 ,0
Exp/Cntr=0.3,0.1

Type RM Length L Ch R = 1 ,4613.4  ,190.5,210.8,228.5
XS GIS Cut Line= 3
     1829159.695       517604.56     1829120.632      517714.803
     1829093.722      517808.553
#Sta/Elev= 25
       0  611.03     9.8  610.86    19.5  609.71    29.2  607.49      39  605.73
    48.7  604.71    54.6  604.29    58.5  604.02    68.2  604.51    69.6  604.94
      78  607.54    87.7  610.58    97.5  611.01   107.2  611.09     117  611.78
   126.7     613   136.5  614.25   146.2  615.52     156  617.21   165.7  619.51
   175.5  622.01   185.2  624.44     195  626.96   204.7  629.52   214.5  632.17
#Mann= 3 , 0 , 0
       0     .06       0    48.7    .045       0    69.6     .06       0
Bank Sta=48.7,69.6
XS Rating Curve= 0 ,0
Exp/Cntr=0.3,0.1

Type RM Length L Ch R = 1 ,4402.6  ,221.4,233.7,245.5
XS GIS Cut Line= 3
     1829106.743      517518.623     1828932.264      517611.505
     1828868.028      517660.984
#Sta/Elev= 24
       0  611.47     9.4  609.87    18.8  609.08    28.2  608.01    37.6  606.64
    47.1  605.95    56.5  605.15    65.9     604    75.3  603.46    84.7  603.52
    94.1  604.56   103.5   607.1     113   608.1   141.2  608.32   150.6  608.66
   188.2  611.06   197.7  612.44   206.7  614.72   224.7  621.09   242.7  627.66
   251.7  631.19   260.7  635.78   269.7  641.13   278.7  646.74
#Mann= 3 , 0 , 0
       0     .06       0    65.9    .045       0    84.7      .1       0
Bank Sta=65.9,84.7
XS Rating Curve= 0 ,0
Exp/Cntr=0.3,0.1

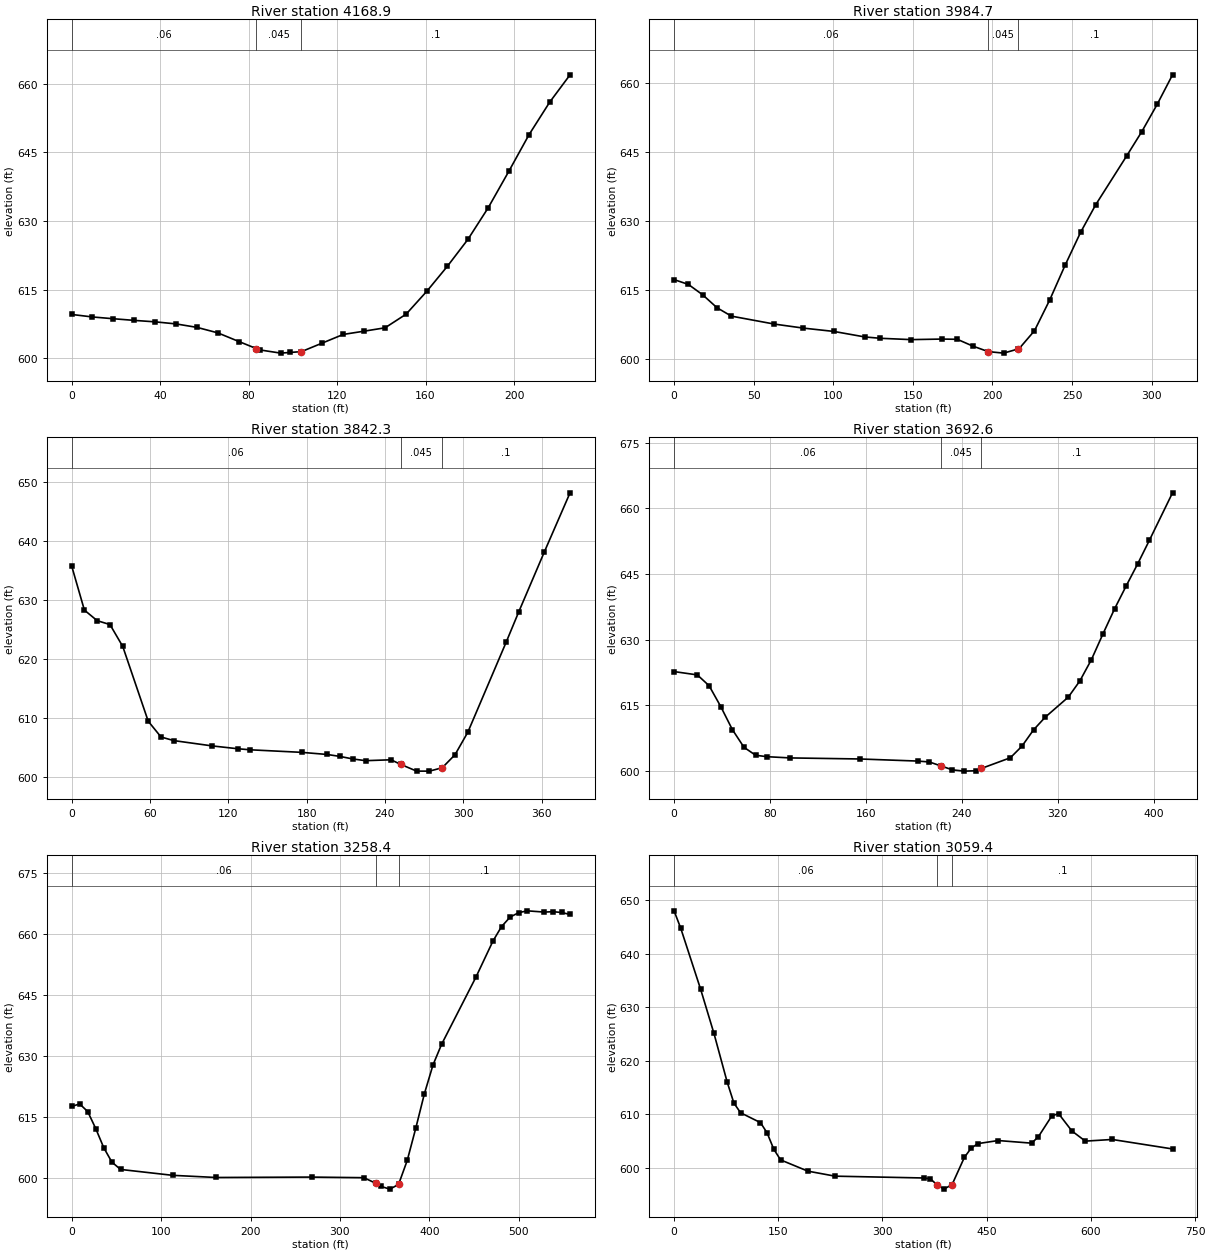
Type RM Length L Ch R = 1 ,4168.9  ,189.5,184.2,176.5
XS GIS Cut Line= 3
     1829059.868      517341.539     1828899.278      517340.671
     1828835.042      517332.859
#Sta/Elev= 27
       0  609.58     9.4  609.03    18.9  608.64    28.3  608.28    37.8  607.96
    47.2  607.51    56.7  606.75    66.1  605.55    75.6  603.66    83.5  602.12
      85  601.83    94.5  601.12    98.5  601.26   103.9  601.45   113.4  603.34
   122.8  605.21   132.2  605.92   141.7  606.66   151.2  609.64   160.6  614.67
   169.8  620.08   179.1  625.97   188.3   632.9   197.6  640.86   206.8  648.92
   216.1     656   225.3  661.98
#Mann= 3 , 0 , 0
       0     .06       0    83.5    .045       0   103.9      .1       0
Bank Sta=83.5,103.9
XS Rating Curve= 0 ,0
Exp/Cntr=0.3,0.1

Type RM Length L Ch R = 1 ,3984.7  ,152.2,142.4,134.5
XS GIS Cut Line= 4
      1829090.25      517161.852     1829010.389      517147.963
     1828868.896      517180.949     1828794.243       517225.22
#Sta/Elev= 27
       0  617.18       9  616.13      18  613.86      27  611.05      36  609.23
      63   607.5    81.1  606.63   100.4   605.9   119.8   604.7   129.5  604.41
   148.9  604.12   168.2  604.24   177.9  604.19   187.6  602.72   197.3  601.51
     207  601.18     216  602.07   216.7  602.14   226.4  606.06     236  612.78
   245.6  620.29   255.3  627.43   264.9   633.5   284.2  644.04   293.8  649.38
   303.5  655.34   313.1  661.74
#Mann= 3 , 0 , 0
       0     .06       0   197.3    .045       0     216      .1       0
Bank Sta=197.3,216
XS Rating Curve= 0 ,0
Exp/Cntr=0.3,0.1

Type RM Length L Ch R = 1 ,3842.3  ,150.2,149.7,149.2
XS GIS Cut Line= 2
     1829031.222      516893.623     1828726.535      517123.657
#Sta/Elev= 27
       0  635.78     9.8  628.26    19.6  626.47    29.4  625.81    39.2   622.1
    58.7  609.44    68.5  606.77    78.3  606.16   107.7  605.26   127.3  604.78
     137   604.6   176.2  604.17   195.8  603.81   205.6  603.48   215.4  603.05
   225.2  602.76   244.7  602.91     252  602.14   264.3  600.99   274.1  600.99
   283.9  601.56   293.7  603.77   303.5  607.58   332.8  622.79   342.6  628.01
   362.2  638.16   381.8  648.12
#Mann= 3 , 0 , 0
       0     .06       0     252    .045       0   283.9      .1       0
Bank Sta=252,283.9
XS Rating Curve= 0 ,0
Exp/Cntr=0.3,0.1

Type RM Length L Ch R = 1 ,3692.6  ,403.3,434.2,465
XS GIS Cut Line= 3
     1828924.596      516778.171     1828883.364      516819.404
     1828601.246      517038.588
#Sta/Elev= 30
       0  622.67    19.4  621.91    29.2  619.44    38.9  614.68    48.6   609.4
    58.3  605.35      68  603.53    77.6   603.2    96.9  602.92   154.9  602.68
   203.2   602.2   212.8     602   222.5  601.09   232.1  600.19   241.8   599.9
   251.4  599.98   256.3  600.52   280.4  602.96     290  605.59   299.7  609.33
   309.4  612.22   328.7  616.83   338.3  620.52     348  625.42   357.6  631.29
   367.3  637.03     377  642.29   386.6  647.34   396.3   652.7   415.6  663.56
#Mann= 3 , 0 , 0
       0     .06       0   222.5    .045       0   256.3      .1       0
Bank Sta=222.5,256.3
XS Rating Curve= 0 ,0
Exp/Cntr=0.3,0.1

Type RM Length L Ch R = 1 ,3258.4  ,198.1,199,199.8
XS GIS Cut Line= 4
      1828916.82      516721.748     1828872.332      516728.258
     1828615.171       516521.01     1828436.476      516486.484
#Sta/Elev= 30
       0  617.59       9  618.22      18  616.35      27  612.16      36  607.44
      45  603.94    54.7  602.12     113  600.67   161.5  600.14   268.4  600.24
   326.7  600.09   339.8  598.74   346.1  597.93   355.8  597.28   365.5  598.43
   375.2  604.33   384.8   612.3   394.4  620.74     404   627.8   413.6  632.87
   451.9  649.34     471  658.24   480.6   661.8   490.2  664.14   499.8  665.23
   509.4  665.68   528.5  665.37   538.1  665.47   547.7  665.27   557.2  664.79
#Mann= 3 , 0 , 0
       0     .06       0   339.8    .045       0   365.5      .1       0
Bank Sta=339.8,365.5
XS Rating Curve= 0 ,0
Exp/Cntr=0.3,0.1

Type RM Length L Ch R = 1 ,3059.4  ,361.9,341.1,320.1
XS GIS Cut Line= 4
     1829056.701      516623.203     1828938.646      516541.606
      1828718.16      516347.161     1828450.798      516263.828
#Sta/Elev= 30
       0  647.99     9.6  644.74    38.3  633.32    57.4  625.11    76.5     616
    86.1  612.11    95.7   610.3   124.4  608.45   133.9  606.54   143.5   603.5
   153.3   601.5   192.5   599.4   231.7  598.46   359.1  598.12   368.9  597.97
   378.7  596.82   388.5  596.04  400.24   596.9   417.9  601.97   427.7   603.7
   437.5  604.54   466.5  605.11   514.7  604.62   524.4  605.82   543.7   609.7
   553.4  610.14   572.7  606.89     592     605   630.6  605.31   717.5  603.54
#Mann= 3 , 0 , 0
       0     .06       0   378.7    .045       0  400.24      .1       0
Bank Sta=378.7,400.24
XS Rating Curve= 0 ,0
Exp/Cntr=0.3,0.1

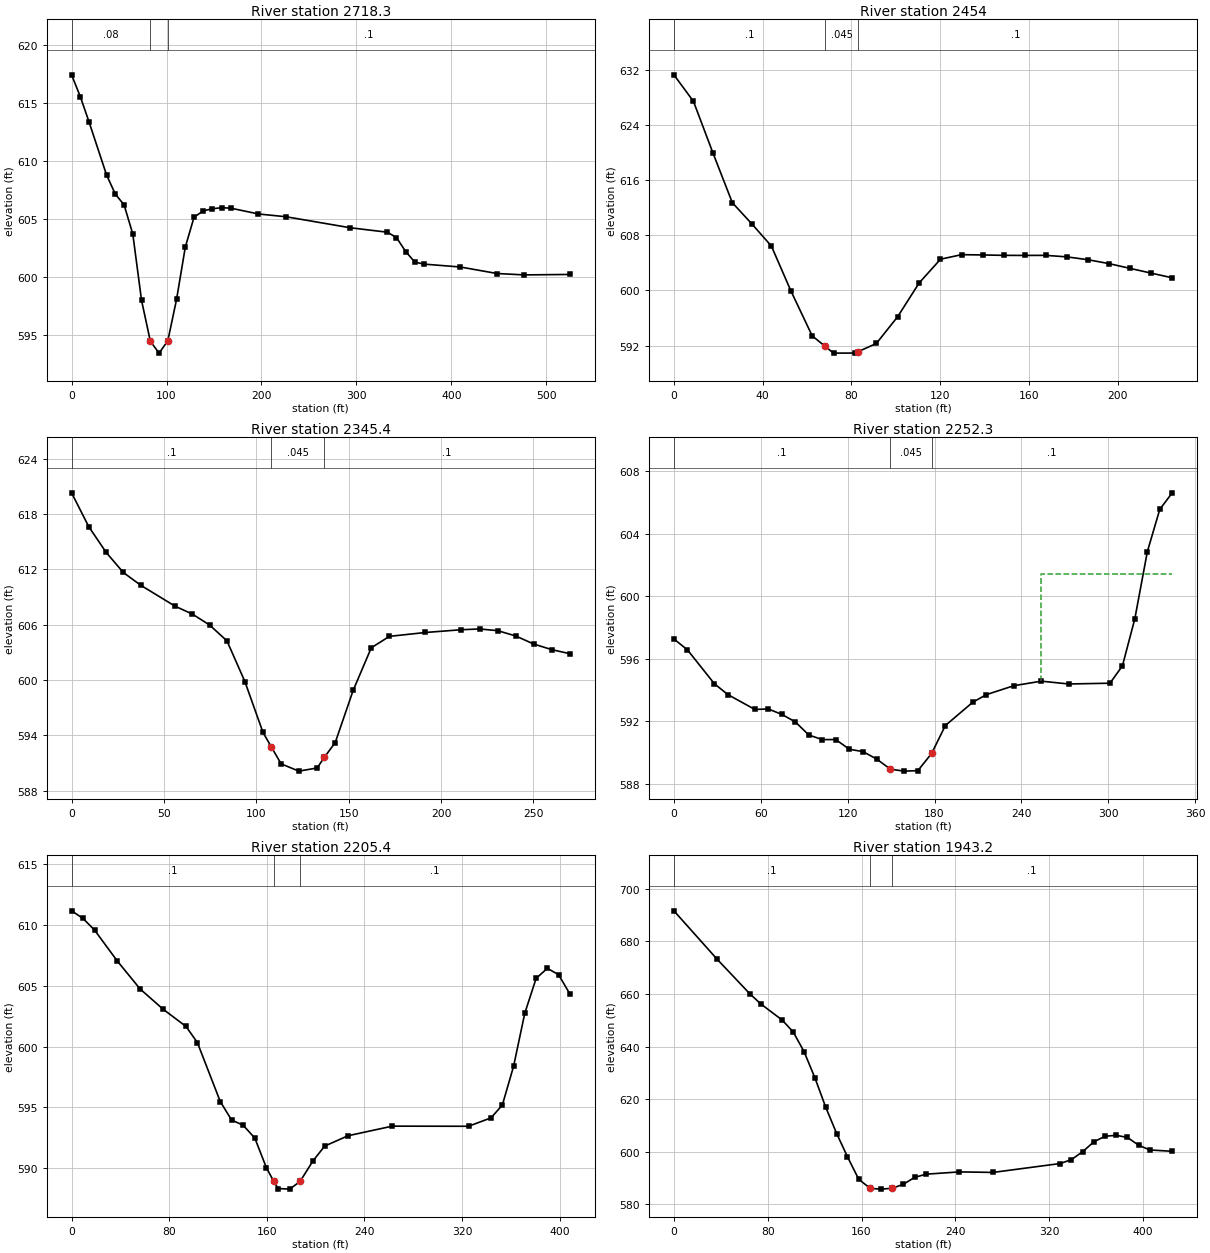
Type RM Length L Ch R = 1 ,2718.3  ,282.3,264.3,245.7
XS GIS Cut Line= 4
     1829041.076      516090.217      1828914.34      516114.522
     1828681.701      516116.259     1828518.507      516109.314
#Sta/Elev= 30
       0  617.44     9.2  615.56    18.4  613.38    36.9   608.8    46.1  607.16
    55.3  606.24    64.5  603.72    73.7  598.01      83  594.48    92.2  593.46
   101.4  594.53   110.6  598.09   119.8  602.59     129  605.17   138.7  605.72
   148.4   605.9   158.1  605.99   167.8  605.95   196.9  605.45     226  605.21
   293.8  604.26   332.6  603.88   342.3  603.42     352  602.21   361.7   601.3
   371.3  601.13   409.7  600.88   448.2  600.32     477   600.2     525  600.24
#Mann= 3 , 0 , 0
       0     .08       0      83    .045       0   101.4      .1       0
Bank Sta=83,101.4
XS Rating Curve= 0 ,0
Exp/Cntr=0.3,0.1

Type RM Length L Ch R = 1 ,2454    ,106.2,108.6,111.5
XS GIS Cut Line= 4
     1828792.037      515894.925     1828763.825      515939.412
     1828726.933      515995.836     1828662.914      516078.301
#Sta/Elev= 27
       0  631.32     8.8  627.47    17.6  619.96    26.3  612.76    35.1  609.67
    43.9  606.46    52.7  599.94    62.3  593.41    68.1  591.89    71.9   590.9
    81.6  590.91    83.1  591.13    91.2   592.3   100.8  596.19   110.5   601.1
   120.1  604.54   129.6   605.2   139.1  605.16   148.6   605.1   158.1  605.09
   167.6   605.1     177  604.88   186.5  604.47     196   603.9   205.5  603.21
     215  602.52   224.5  601.84
#Mann= 3 , 0 , 0
       0      .1       0    68.1    .045       0    83.1      .1       0
Bank Sta=68.1,83.1
XS Rating Curve= 0 ,0
Exp/Cntr=0.3,0.1

Type RM Length L Ch R = 1 ,2345.4  ,93.1,93.1,93.1
XS GIS Cut Line= 3
     1828729.103       515818.97     1828675.934      515884.074
     1828556.577      516026.218
#Sta/Elev= 28
       0  620.29     9.3  616.62    18.7  613.84      28  611.66    37.4  610.28
      56  608.01    65.4  607.15    74.7  605.97    84.1  604.25    93.8  599.84
   103.6  594.33     108   592.8   113.4  590.93     123  590.14   132.9  590.48
  136.85  591.65   142.7  593.24   152.4  598.89   162.2   603.5     172  604.74
   191.5  605.16     211  605.46   220.8  605.54   230.6  605.36   240.4  604.78
   250.1  603.91   259.9   603.3   269.7  602.86
#Mann= 3 , 0 , 0
       0      .1       0     108    .045       0  136.85      .1       0
Bank Sta=108,136.85
XS Rating Curve= 0 ,0
Exp/Cntr=0.3,0.1

Type RM Length L Ch R = 1 ,2252.3  ,57.1,47,36.8
XS GIS Cut Line= 4
     1828686.785      515723.484      1828610.83      515817.885
      1828495.08      515955.733      1828525.22      515986.412
#Sta/Elev= 30
       0  597.27     9.3  596.58      28   594.4    37.3  593.71    55.9  592.76
    65.2  592.79    74.6  592.44    83.9  591.96    93.2  591.12   102.5  590.83
   111.8  590.83   121.2  590.21   130.6  590.06   140.1  589.58   149.6  588.93
   159.1  588.81   168.5  588.84     178  589.94   187.5  591.73   206.4  593.22
   215.9  593.71   234.8  594.28   253.8  594.57   272.7  594.39   301.2  594.44
   309.8  595.55   318.4  598.58     327  602.86   335.6  605.57   344.2  606.63
#Mann= 3 , 0 , 0
       0      .1       0   149.6    .045       0     178      .1       0
#XS Ineff= 2 , 0
                          253.28          601.45
Permanent Ineff=
       F       F
Bank Sta=149.6,178
XS Rating Curve= 0 ,0
Exp/Cntr=0.3,0.1

Type RM Length L Ch R = 1 ,2205.4  ,286.1,262.2,238.3
XS GIS Cut Line= 5
     1828538.689      515651.675     1828550.066      515791.843
      1828525.11      515884.074     1828470.287      515954.412
     1828527.303      516014.884
#Sta/Elev= 30
       0  611.17     9.4  610.54    18.8  609.59    37.5  607.04    56.2  604.74
      75  603.08    93.8  601.66   103.1  600.34   121.9  595.48   131.2  593.96
   140.6  593.54   150.2  592.48   159.7  590.04  165.63  588.94   169.3  588.33
   178.8  588.28   187.3  588.91     198  590.62   207.5  591.82   226.6  592.67
   262.9  593.46   325.4  593.45   343.8  594.14   353.1  595.19   362.3  598.37
   371.5  602.74   380.8  605.61     390  606.44   399.2  605.92   408.5  604.33
#Mann= 3 , 0 , 0
       0      .1       0  165.63    .045       0   187.3      .1       0
Bank Sta=165.63,187.3
XS Rating Curve= 0 ,0
Exp/Cntr=0.3,0.1

Type RM Length L Ch R = 1 ,1943.2  ,124.1,108.7,92.3
XS GIS Cut Line= 3
      1828245.72      515760.182     1828307.011      515894.925
     1828502.323      516091.322
#Sta/Elev= 30
       0  691.57      37  673.11    64.8  660.02      74  656.24    92.5  650.01
   101.8   645.5     111  638.07   120.3  628.06   129.5  616.92   138.8  606.96
     148  598.14   157.6  589.59   167.4  586.12   176.7  585.83   186.2  586.16
   195.8   587.7   205.3  590.29   214.9   591.5   243.5  592.38   272.2  592.18
   329.5  595.56     339  597.04   348.6  600.06   358.2  603.81   367.7  605.92
   377.2  606.28   386.8  605.46   396.4  602.51   405.9  600.71     425   600.2
#Mann= 3 , 0 , 0
       0      .1       0   167.4    .045       0   186.2      .1       0
Bank Sta=167.4,186.2
XS Rating Curve= 0 ,0
Exp/Cntr=0.3,0.1

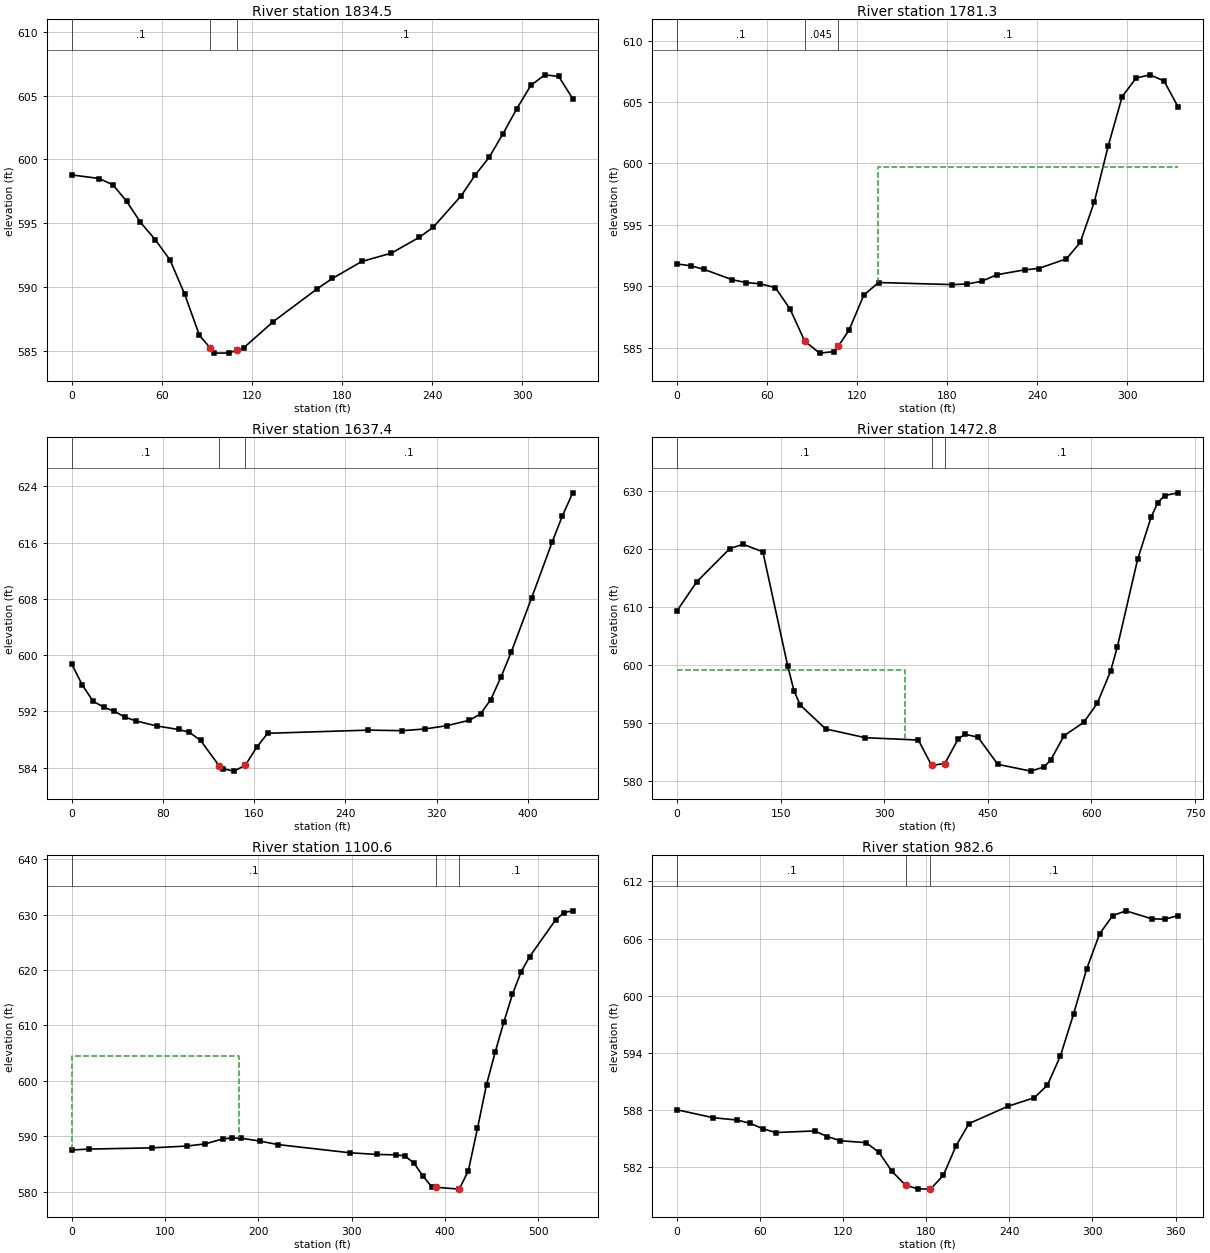
Type RM Length L Ch R = 1 ,1834.5  ,52.9,53.3,52.9
XS GIS Cut Line= 4
     1828155.381      515977.655     1828199.826      515988.767
     1828365.103      516013.072     1828453.298      516095.711
#Sta/Elev= 30
       0  598.79    18.3  598.51    27.5  598.01    36.6  596.72    45.8  595.08
    55.6  593.73    65.5  592.13    75.3  589.44    85.1  586.23   92.38  585.24
      95  584.85   104.8  584.86     110  585.08   114.6  585.27   134.2  587.31
   163.7   589.9   173.6  590.69   193.2  592.02   212.9  592.67   231.5  593.91
   240.8   594.7   259.4  597.16   268.6  598.76     278  600.16   287.2     602
   296.5  603.98   305.8  605.79   315.1  606.62   324.4  606.49   333.7  604.75
#Mann= 3 , 0 , 0
       0      .1       0   92.38    .045       0     110      .1       0
Bank Sta=92.38,110
XS Rating Curve= 0 ,0
Exp/Cntr=0.3,0.1

Type RM Length L Ch R = 1 ,1781.3  ,113.5,143.9,175.8
XS GIS Cut Line= 4
     1828133.159      516020.017     1828177.603      516031.128
     1828342.881      516055.433     1828431.076      516138.072
#Sta/Elev= 30
       0  591.81     9.2  591.66    18.3  591.36    36.6  590.53    45.8   590.3
    55.6  590.19    65.5  589.88    75.3  588.14    85.1  585.52      95  584.55
   104.8  584.68  107.26  585.09   114.6  586.43   124.4  589.27   134.2   590.3
   183.4  590.13   193.2  590.18     203   590.4   212.9  590.93   231.5  591.33
   240.8  591.44   259.4  592.23   268.6  593.57     278  596.89   287.2  601.42
   296.5  605.44   305.8  606.95   315.1  607.21   324.4  606.71   333.7   604.6
#Mann= 3 , 0 , 0
       0      .1       0    85.1    .045       0  107.26      .1       0
#XS Ineff= 2 , 0
                          133.92          599.67
Permanent Ineff=
       F       F
Bank Sta=85.1,107.26
XS Rating Curve= 0 ,0
Exp/Cntr=0.3,0.1

Type RM Length L Ch R = 1 ,1637.4  ,176.2,164.5,347.8
XS GIS Cut Line= 4
     1828105.188      515974.135     1828101.933      516077.216
     1828130.145      516331.123     1828146.421      516410.333
#Sta/Elev= 30
       0  598.73     9.4  595.72    18.8  593.44    28.1   592.6    37.5  592.01
    46.9  591.18    56.2  590.65      75  589.92    93.8  589.43   103.1  589.04
     113  587.88  129.32  584.27   132.6  583.85   142.4  583.51   152.3  584.34
   162.1  586.87   171.9  588.89   260.3  589.34   289.8  589.26   309.5   589.5
   329.1  589.97   348.8  590.74   358.6  591.64   367.6  593.68   376.6   596.9
   385.6  600.46   403.5  608.17   421.5   616.1   430.5  619.83   439.5  623.08
#Mann= 3 , 0 , 0
       0      .1       0  129.32    .045       0   152.3      .1       0
Bank Sta=129.32,152.3
XS Rating Curve= 0 ,0
Exp/Cntr=0.3,0.1

Type RM Length L Ch R = 1 ,1472.8  ,373.1,372.2,175.1
XS GIS Cut Line= 6
     1827732.443      515897.049     1827855.119      515916.946
     1827896.116      515987.082     1827923.981      516118.449
     1828075.891      516327.867     1828091.082      516453.735
#Sta/Elev= 30
       0  609.41    28.7  614.43    76.5  620.14    95.6  620.88   124.3  619.58
   160.4  599.82   169.4   595.6   178.4  593.16   215.1  589.05   272.7  587.53
   349.4  587.13   368.6  582.76   387.7  583.08   406.9  587.28   416.5  588.13
   435.6  587.63   464.4  582.94   512.3  581.77   531.4   582.5     541  583.69
   560.2  587.87   588.9  590.19   608.3  593.45   627.8  599.04   637.5  603.21
   666.8  618.28   686.3  625.55     696  628.06   705.8  629.28   725.3  629.75
#Mann= 3 , 0 , 0
       0      .1       0   368.6    .045       0   387.7      .1       0
#XS Ineff= 2 , 0
           329.5   599.2
Permanent Ineff=
       F       F
Bank Sta=368.6,387.7
XS Rating Curve= 0 ,0
Exp/Cntr=0.3,0.1

Type RM Length L Ch R = 1 ,1100.6  ,113.6,118,122.3
XS GIS Cut Line= 5
     1827754.144      516075.001     1827809.042       516175.02
     1827875.133      516325.822       1827979.3      516454.945
     1828068.296      516479.777
#Sta/Elev= 30
       0  587.52      19  587.68    85.6   587.9   123.8  588.23   143.2  588.62
   162.5  589.55   172.2  589.66   181.9  589.63   201.3  589.14   220.6   588.5
   298.3  587.01   327.5  586.71   347.1  586.64   356.8  586.46   366.6   585.2
   376.3  582.86   386.1  580.81   390.9  580.78   415.4  580.45   425.1  583.76
   434.9  591.42   444.6  599.32   453.9  605.19   463.1  610.58   472.4  615.62
   481.6  619.64   490.8  622.42   518.6  629.05   527.8  630.38     537  630.69
#Mann= 3 , 0 , 0
       0      .1       0   390.9    .045       0   415.4      .1       0
#XS Ineff= 2 , 0
           179.1  604.57
Permanent Ineff=
       F       F
Bank Sta=390.9,415.4
XS Rating Curve= 0 ,0
Exp/Cntr=0.3,0.1

Type RM Length L Ch R = 1 ,982.6   ,168.4,200,231.7
XS GIS Cut Line= 4
     1827817.645      516345.228     1827815.474      516388.631
     1827894.684      516536.201      1827895.77      516687.025
#Sta/Elev= 30
       0  588.03    26.1   587.2    43.5  586.95    52.8  586.61    62.1  586.03
    71.4  585.64    99.3  585.81   108.6  585.22   117.9  584.78   136.5  584.58
   145.8  583.57   155.1  581.59   165.1   580.1   173.7  579.74     183   579.7
   192.3  581.14   201.6  584.27   210.9  586.59   239.2  588.41   258.1   589.3
   267.5  590.63   276.9   593.7   286.4   598.1   295.8  602.81   305.2  606.51
   314.6  608.41   324.1  608.92   342.9  608.08   352.3  608.04   361.8  608.42
#Mann= 3 , 0 , 0
       0      .1       0   165.1    .045       0     183      .1       0
Bank Sta=165.1,183
XS Rating Curve= 0 ,0
Exp/Cntr=0.3,0.1

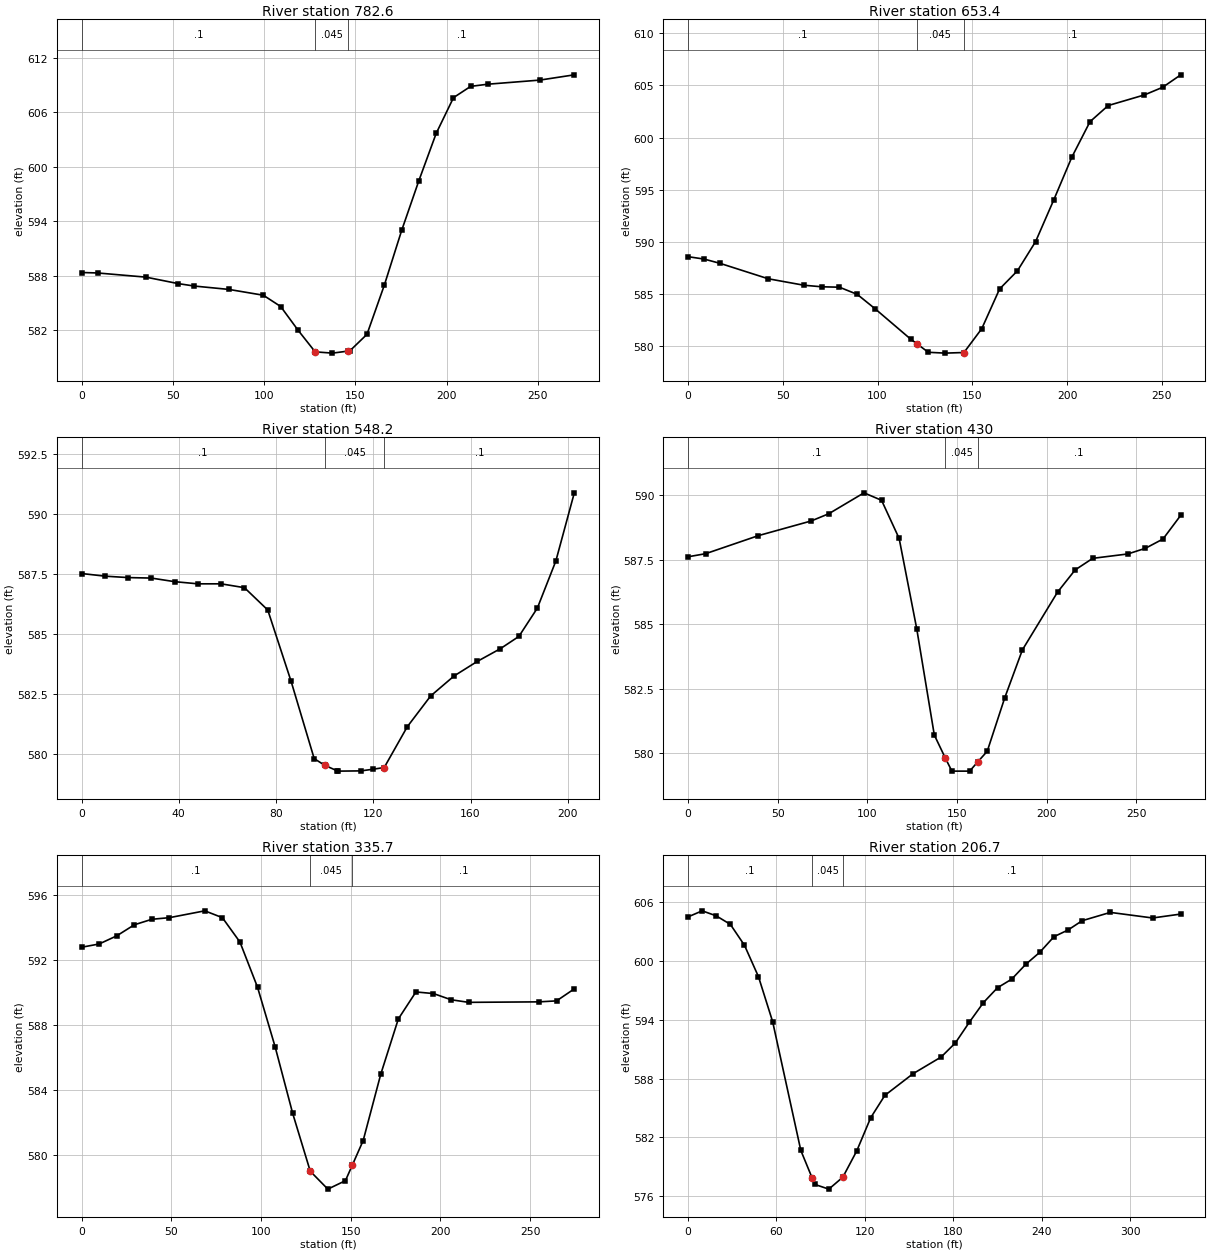
Type RM Length L Ch R = 1 ,782.6   ,120,129.2,137.9
XS GIS Cut Line= 3
     1827816.559      516315.932     1827797.028      516374.525
     1827635.353      516505.819
#Sta/Elev= 23
       0  588.38     8.8  588.33    35.3  587.87    52.9  587.16    61.8  586.89
    80.7  586.52    99.6  585.88   109.1  584.64   118.6  582.04     128  579.65
   137.5  579.51   146.2  579.74     147  579.76   156.4  581.58   165.9  586.99
   175.4  593.01   184.8  598.47   194.3  603.68   203.8  607.62   213.2  608.86
   222.7   609.1   251.1  609.55     270  610.13
#Mann= 3 , 0 , 0
       0      .1       0     128    .045       0   146.2      .1       0
Bank Sta=128,146.2
XS Rating Curve= 0 ,0
Exp/Cntr=0.3,0.1

Type RM Length L Ch R = 1 ,653.4   ,108.2,105.2,102.2
XS GIS Cut Line= 4
     1827817.645      516276.869     1827775.327      516277.954
     1827649.459      516315.932     1827575.674      516360.419
#Sta/Elev= 25
       0  588.56     8.5  588.33    16.9  587.92    42.3  586.44    61.1  585.82
    70.5  585.67    79.9  585.63    89.3  584.94    98.7  583.56   117.5  580.64
   120.7  580.21   126.8  579.38   135.7   579.3   145.6  579.36     155  581.65
   164.4  585.46   173.8   587.2   183.4  590.01     193  594.02   202.5  598.11
   212.1  601.52   221.7  603.07   240.8  604.09   250.4  604.82     260  606.02
#Mann= 3 , 0 , 0
       0      .1       0   120.7    .045       0   145.6      .1       0
Bank Sta=120.7,145.6
XS Rating Curve= 0 ,0
Exp/Cntr=0.3,0.1

Type RM Length L Ch R = 1 ,548.2   ,145.2,118.2,91.3
XS GIS Cut Line= 3
     1827760.136      516157.511     1827603.219      516228.743
     1827586.525      516254.083
#Sta/Elev= 26
       0  587.53     9.6  587.42    19.2  587.36    28.7  587.34    38.3  587.19
    47.9   587.1    57.4   587.1      67  586.94    76.6  586.01    86.2  583.04
    95.7  579.82  100.09  579.54     105  579.32   105.3   579.3   114.9  579.31
     120  579.38   124.5  579.45     134  581.15   143.6  582.43   153.2  583.26
   162.8  583.87   172.3   584.4   179.9  584.91   187.5  586.09   195.1  588.05
   202.7  590.89
#Mann= 3 , 0 , 0
       0      .1       0  100.09    .045       0   124.5      .1       0
Bank Sta=100.09,124.5
XS Rating Curve= 0 ,0
Exp/Cntr=0.3,0.1

Type RM Length L Ch R = 1 ,430     ,94.2,94.3,94.3
XS GIS Cut Line= 2
     1827576.759      515968.709      1827585.44      516243.232
#Sta/Elev= 24
       0  587.61     9.8  587.73    39.2  588.43    68.7     589    78.5  589.28
    98.1  590.09   107.9   589.8   117.7  588.32   127.5  584.82   137.3   580.7
  143.49   579.8   147.1   579.3     157   579.3   161.4  579.65   166.8  580.07
   176.6  582.15   186.4     584     206  586.24   215.8   587.1   225.6  587.55
   245.2  587.72     255  587.94   264.8   588.3   274.7  589.22
#Mann= 3 , 0 , 0
       0      .1       0  143.49    .045       0   161.4      .1       0
Bank Sta=143.49,161.4
XS Rating Curve= 0 ,0
Exp/Cntr=0.3,0.1

Type RM Length L Ch R = 1 ,335.7   ,135,129,123.3
XS GIS Cut Line= 2
     1827483.443      515968.709     1827492.124      516243.232
#Sta/Elev= 26
       0  592.76     9.8  592.96    19.6  593.46    29.4  594.14    39.2  594.48
      49  594.58    68.7     595    78.5  594.58    88.3  593.08    98.1   590.3
   107.9  586.64   117.7  582.54   127.5  578.98   137.3  577.88   147.1   578.4
     151  579.37     157  580.87   166.8  584.95   176.6  588.35   186.4  590.01
   196.2  589.91     206  589.53   215.8  589.37     255   589.4   264.8  589.46
   274.7   590.2
#Mann= 3 , 0 , 0
       0      .1       0   127.5    .045       0     151      .1       0
Bank Sta=127.5,151
XS Rating Curve= 0 ,0
Exp/Cntr=0.3,0.1

Type RM Length L Ch R = 1 ,206.7   ,207.6,206.7,205.6
XS GIS Cut Line= 4
     1827330.448      516015.367      1827354.32      516088.067
     1827367.341       516133.64     1827475.848      516313.761
#Sta/Elev= 30
       0  604.51     9.6  605.13    19.1  604.62    28.7  603.75    38.3  601.61
    47.8   598.4    57.4  593.81    76.5  580.67   84.32  577.81      86   577.2
    95.5  576.72     105  577.94   114.4  580.61   123.9  584.01   133.5  586.29
   152.6   588.5   171.7  590.21   181.3  591.64   190.8  593.76   200.4  595.77
   209.9  597.28   219.5  598.15     229  599.66   238.6   600.9   248.2  602.49
   257.7  603.17   267.3  604.12   286.4  604.97   315.1   604.4   334.2   604.8
#Mann= 3 , 0 , 0
       0      .1       0   84.32    .045       0     105      .1       0
Bank Sta=84.32,105
XS Rating Curve= 0 ,0
Exp/Cntr=0.3,0.1

Chan Stop Cuts=-1
Use User Specified Reach Order=0
Composite Channel Slope=5